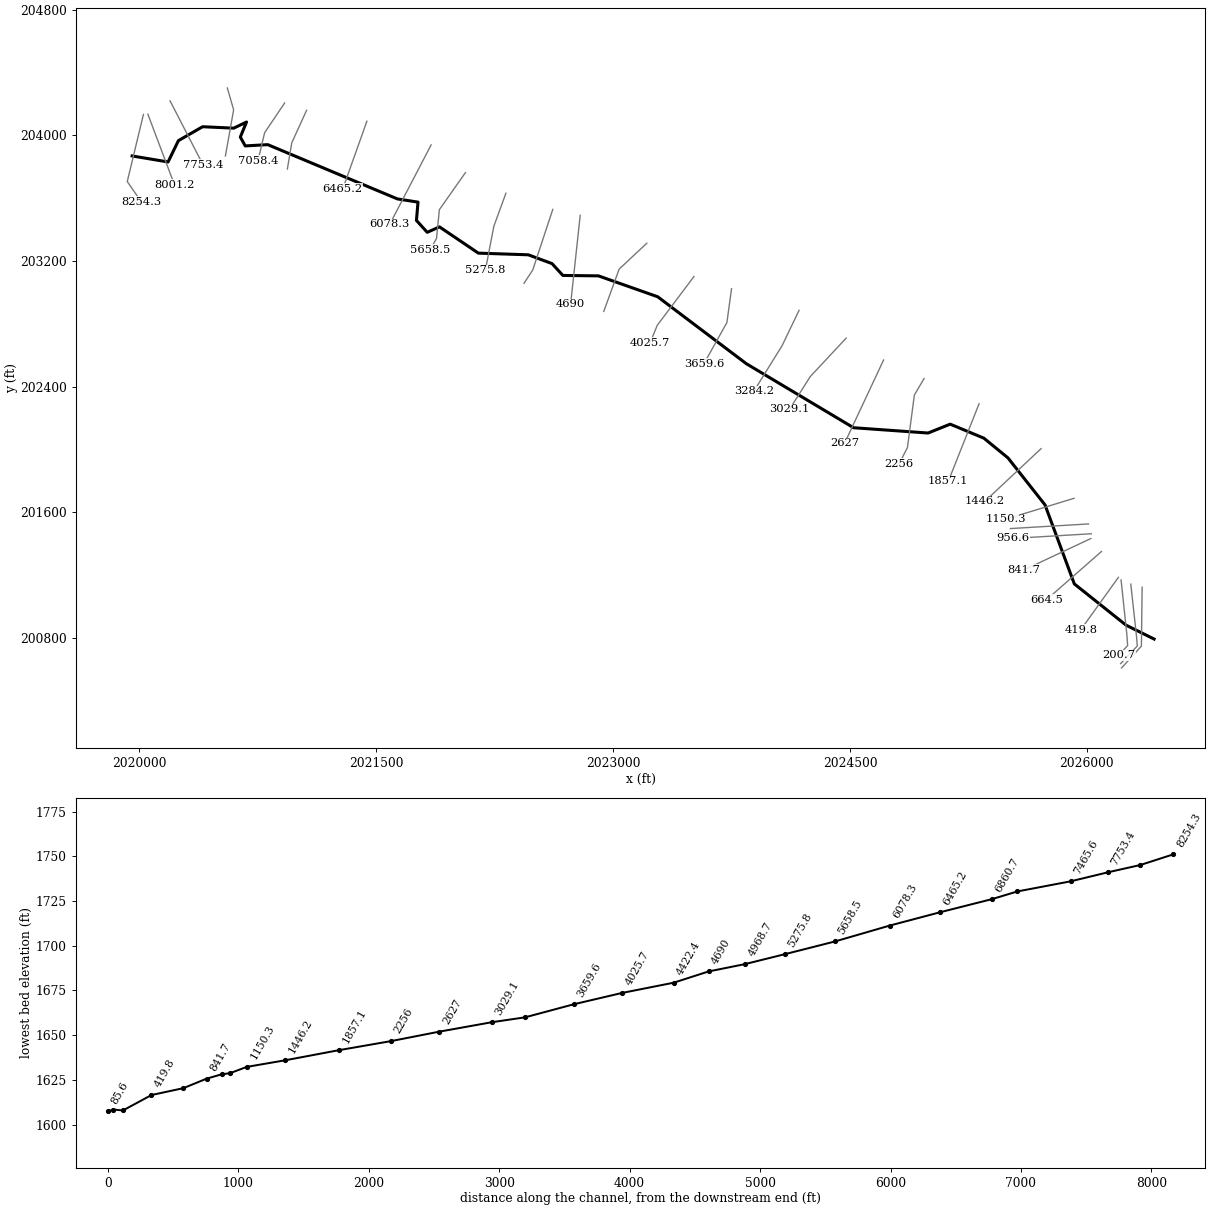
--- JNYCKFK.prj (project) ---

Proj Title=JNYCKFK
Current Plan=p01
Default Exp/Contr=0,0
English Units
Geom File=g01
Flow File=f01
Plan File=p01
BEGIN DESCRIPTION:
END DESCRIPTION:
DSS Export Rating Curves= 0
DSS Export Rating Curve Sorted= 0
DSS Export Volume Flow Curves= 0
DXF OffsetX= 0
DXF OffsetY= 0
DXF ScaleX= 0
DXF ScaleY= 0

--- JNYCKFK.p01 (plan) ---

Plan Title=Floodplain
Program Version=4.00
Geom File=g01
Flow File=f01
K Sum by GR=0
Std Step Tol=0.01
Critical Tol=0.01
Num of Std Step Trials=20
Max Error Tol=0.3
Flow Tol Ratio=0.001
Split Flow NTrial=30
Split Flow Tol=0.02
Split Flow Ratio=0.02
Log Output Level=0
Friction Slope Method=1
Unsteady Friction Slope Method=2
Unsteady Bridges Friction Slope Method=1
Global Log Level=0
CheckData=False
Run HTab=0
Run UNet=0
Run PostProcess=0
UNET Theta=0
UNET Theta Warmup=0
UNET ZTol=0
UNET ZSATol=0
UNET MxIter=0
UNET MaxInSteps=0
UNET DtIC=0
UNET DtMin=0
UNET MaxCRTS=0
UNET WFStab=0
UNET SFStab=0
UNET WFX=0
UNET SFX=0
UNET DSS MLevel=0
UNET DZMax Abort=0
UNET Convert EG Bridges=0
UNET Use Existing IB Tables=0
UNET Froude Limit=0
UNET Froude Power=0
Write IC File=0
Echo Input=False
Echo Output=False
Write Detailed=0

--- JNYCKFK.f01 (steady flow) ---

Flow Title=NFF Regression Equation
Program Version=4.10
Number of Profiles= 1
Profile Names=P100yr
River Rch & RM=JNYCKFK,Main            ,8254.3
699.5652
River Rch & RM=JNYCKFK,Main            ,7465.6
703.4151
River Rch & RM=JNYCKFK,Main            ,6860.7
931.1206
River Rch & RM=JNYCKFK,Main            ,841.7
1022.263
River Rch & RM=JNYCKFK,Main            ,419.8
1024.828
Boundary for River Rch & Prof#=JNYCKFK,Main            , 1
Up Type= 0
Dn Type= 3
Dn Slope=0.028
DSS Import GetInterval= 0
DSS Import GetPeak= 0
DSS Import FillOption= 0

--- JNYCKFK.g01 (geometry) ---

Geom Title=USGS 1m DEM
Program Version=4.10

River Reach=JNYCKFK         ,Main
Reach XY= 30
     2019954.481      203868.536     2020182.039       203830.22
     2020247.684       203966.07     2020400.857      204054.509
     2020597.794      204045.392     2020678.939      204084.597
     2020639.734      203988.864     2020670.733      203932.336
     2020812.965      203940.541     2021634.446      203594.991
     2021764.749      203574.729     2021754.796      203458.229
     2021823.177      203382.555     2021900.675      203417.201
     2022146.872      203250.043     2022463.007      203239.445
     2022613.561      203183.376     2022682.039       203108.12
     2022907.239      203105.385     2023282.325      202972.447
       2023843.6      202546.486     2024522.849      202138.937
     2024994.465      202105.333     2025134.628       202161.73
     2025347.976      202072.379     2025500.503      201946.899
     2025734.796      201648.292     2025920.551      201145.136
     2026247.809      200882.859     2026425.562       200794.27

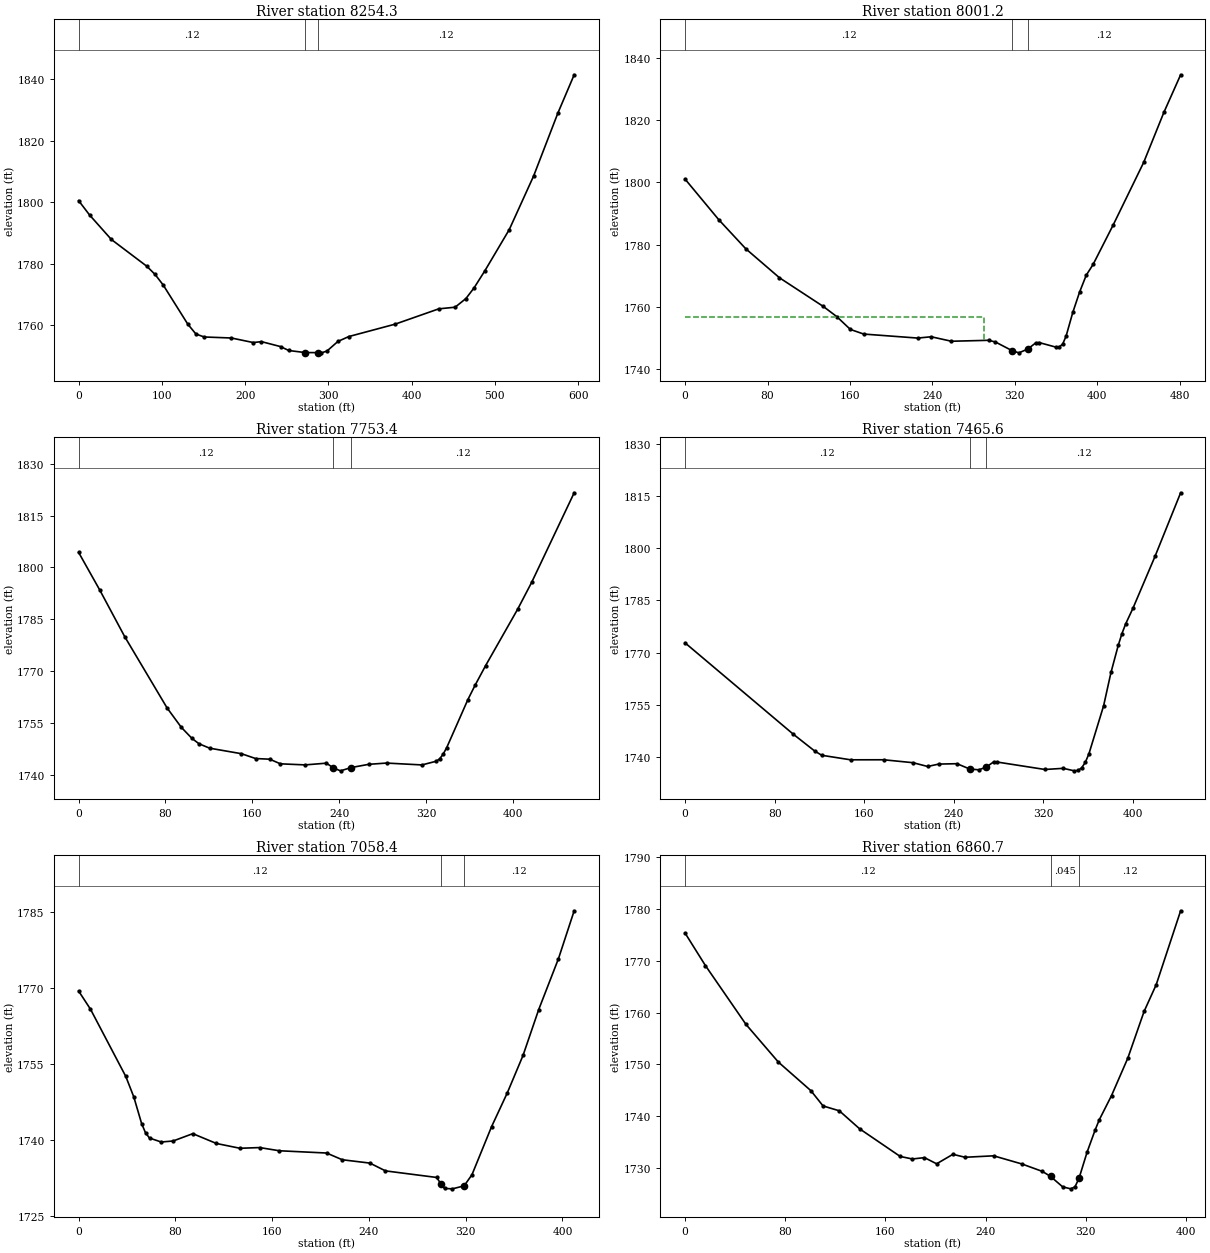
Type RM Length L Ch R = 1 ,8254.3  ,196,253.2,268
XS GIS Cut Line= 3
      2020026.13      204132.685     2019923.699      203705.601
     2020012.241      203577.129
#Sta/Elev= 30
       0 1800.55    13.1  1795.9    39.3 1787.94    81.9 1779.24    91.8 1776.59
   101.6 1773.14   131.1 1760.44   140.9 1757.23   150.8 1756.27   183.5 1755.94
   209.8 1754.46   219.6 1754.76   242.5 1753.15   252.4 1751.88     272 1751.21
     287 1751.19   291.7 1751.12   298.3 1751.71   311.4 1754.82   324.5 1756.41
   380.2 1760.44   432.6 1765.41   452.2 1765.94   465.2 1768.76     475 1772.23
     488  1777.8   517.2 1791.13   546.5 1808.56   575.7 1829.04   595.2 1841.43
#Mann= 3 ,-1 , 0
       0     .12       0     272    .045       0     287     .12       0
Bank Sta=272,287
XS Rating Curve= 0 ,0
Exp/Cntr=0.3,0.1

Type RM Length L Ch R = 1 ,8001.2  ,269.7,247.8,250.2
XS GIS Cut Line= 2
     2020054.342      204134.168     2020223.033       203683.66
#Sta/Elev= 30
       0 1801.02    32.7 1787.97    58.9 1778.63    91.6  1769.3   134.2 1760.06
   147.3 1756.78   160.4 1752.68   173.4 1751.19   225.8  1749.9   238.9 1750.32
   258.5 1748.88   294.5 1749.18   301.1 1748.66   317.6 1745.82     324 1745.15
   332.6 1746.37   340.3 1748.34   343.6 1748.46     360 1746.98   363.2 1747.06
   366.5 1747.97   369.8 1750.51   376.3 1758.14   382.9 1764.68   389.4 1770.14
     396 1773.57   415.6 1786.33   445.1 1806.39   464.7 1822.48     481  1834.6
#Mann= 3 ,-1 , 0
       0     .12       0   317.6    .045       0   332.6     .12       0
#XS Ineff= 2 , 0
           290.4 1756.67
Permanent Ineff=
       F       F
Bank Sta=317.6,332.6
XS Rating Curve= 0 ,0
Exp/Cntr=0.3,0.1

Type RM Length L Ch R = 1 ,7753.4  ,312.3,287.7,263.1
XS GIS Cut Line= 2
     2020194.532       204219.49     2020402.866       203813.24
#Sta/Elev= 30
       0 1804.31    19.6 1793.35    42.4 1779.96    81.5 1759.29    94.6 1753.68
   104.4 1750.48   110.9 1748.92   120.7 1747.64     150 1746.04   163.1 1744.64
   176.1 1744.45   185.9 1743.11   208.7  1742.8   228.3  1743.3   234.8 1741.91
   241.3 1741.08   251.1 1742.03   267.4 1742.97   283.7 1743.33   316.3 1742.79
   329.4 1743.85   332.6 1744.53   335.9 1745.92   339.2 1747.83   358.7 1761.73
   365.2  1765.8     375 1771.55   404.4  1787.8   417.4 1795.62   456.6 1821.58
#Mann= 3 ,-1 , 0
       0     .12       0   234.8    .045       0   251.1     .12       0
Bank Sta=234.8,251.1
XS Rating Curve= 0 ,0
Exp/Cntr=0.3,0.1

Type RM Length L Ch R = 1 ,7465.6  ,410.8,407.2,284
XS GIS Cut Line= 3
      2020557.38      204301.087      2020597.31      204162.198
     2020545.227      203868.796
#Sta/Elev= 30
       0 1772.76    96.3 1746.61   115.6 1741.72     122 1740.47   147.8 1739.17
   177.3 1739.18   203.5 1738.34   216.6 1737.25   226.4 1737.94   242.8 1738.05
   254.1 1736.53   262.4 1736.29   269.1 1737.13   275.5 1738.56   278.8 1738.52
   321.3 1736.39   337.7 1736.72   347.5    1736   350.8 1736.11   354.1 1736.86
   357.4 1738.45   360.6 1740.89   373.7 1754.67   380.3 1764.27   386.8 1772.08
   390.1 1775.44   393.4 1778.21   399.9  1782.7   419.6  1797.6   442.5 1815.89
#Mann= 3 ,-1 , 0
       0     .12       0   254.1    .045       0   269.1     .12       0
Bank Sta=254.1,269.1
XS Rating Curve= 0 ,0
Exp/Cntr=0.3,0.1

Type RM Length L Ch R = 1 ,7058.4  ,194.6,197.7,200.8
XS GIS Cut Line= 3
     2020920.227      204205.601     2020793.491      204016.365
     2020751.824      203839.282
#Sta/Elev= 30
       0 1769.47     9.8 1765.88      39 1752.58    45.6 1748.54    52.1 1743.25
    55.3 1741.44    58.6  1740.4    68.3 1739.62    78.1 1739.82    94.4 1741.27
   113.9 1739.33   133.4 1738.38   149.7 1738.52   165.9 1737.89     205 1737.44
     218 1736.11   240.8 1735.45   253.7 1733.91     296 1732.61   299.4 1731.39
   302.5 1730.44     309 1730.36   318.7 1730.95   325.2 1733.15   341.4 1742.65
   354.4 1749.33   367.4 1756.73   380.4 1765.82   396.7 1775.86   409.7 1785.34
#Mann= 3 ,-1 , 0
       0     .12       0   299.4    .045       0   318.7     .12       0
Bank Sta=299.4,318.7
XS Rating Curve= 0 ,0
Exp/Cntr=0.3,0.1

Type RM Length L Ch R = 1 ,6860.7  ,401.5,395.5,388.3
XS GIS Cut Line= 3
     2021059.116      204158.726     2020965.366      203952.129
     2020937.588      203785.462
#Sta/Elev= 30
       0 1775.34    16.2 1769.09    48.6 1757.74    74.5 1750.46   100.5 1744.94
   110.2    1742   123.2 1741.06   139.4 1737.59   171.8 1732.26   181.5 1731.77
   191.2 1732.03   200.9 1730.84   213.9 1732.67   223.6  1732.1   246.4 1732.38
   269.1  1730.8   285.4 1729.37   291.9  1728.4   301.6 1726.39   308.1 1726.01
   311.4  1726.4   314.6 1728.02   321.1  1733.1   327.6 1737.42   330.8 1739.32
   340.6    1744   353.6 1751.22   366.6 1760.23   376.3  1765.4   395.8 1779.65
#Mann= 3 ,-1 , 0
       0     .12       0   291.9    .045       0   314.6     .12       0
Bank Sta=291.9,314.6
XS Rating Curve= 0 ,0
Exp/Cntr=0.3,0.1

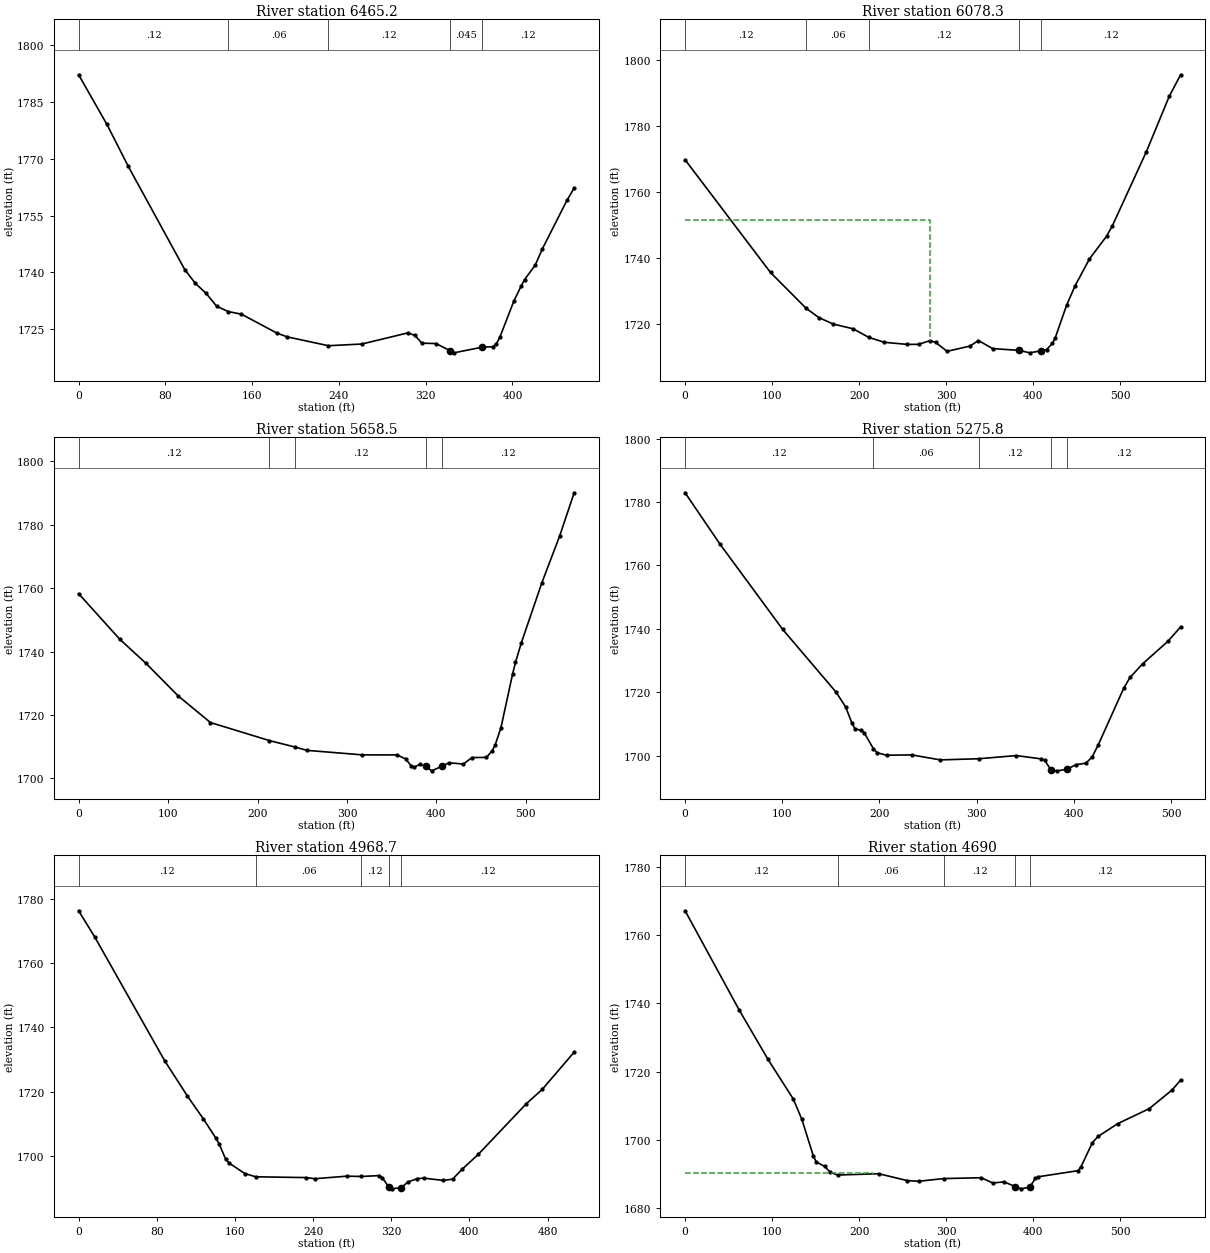
Type RM Length L Ch R = 1 ,6465.2  ,393.1,386.9,380.6
XS GIS Cut Line= 2
      2021441.06      204089.282     2021288.282      203658.726
#Sta/Elev= 30
       0 1792.23    26.1  1779.1    45.7 1768.05    97.9  1740.7   107.7 1737.06
   117.5 1734.45   127.3 1731.02  138.051729.617   150.1 1728.94   182.7 1723.94
   192.5 1722.92  230.381720.592   261.1 1721.04   303.5 1723.98     310 1723.33
   316.5 1721.27   329.6 1721.16   342.6 1719.26   345.9 1718.71     372  1720.2
   381.8 1720.33   385.1 1721.07   388.3 1722.79   401.4 1732.47   407.9  1736.3
   411.2 1738.09     421  1741.9   427.5 1746.16   450.3 1759.06   456.9 1762.28
#Mann= 5 ,-1 , 0
       0     .12       0  138.05     .06       0  230.38     .12       0
   342.6    .045       0     372     .12       0
Bank Sta=342.6,372
XS Rating Curve= 0 ,0
Exp/Cntr=0.3,0.1

Type RM Length L Ch R = 1 ,6078.3  ,379.9,419.8,428.5
XS GIS Cut Line= 2
     2021847.781      203938.746     2021585.628      203433.538
#Sta/Elev= 30
       0 1769.68    98.1 1735.56  138.831724.766   153.7  1721.9   170.1 1719.96
     193 1718.52  211.181715.895     229 1714.42   255.2  1713.8   268.2 1713.81
   281.3 1714.94   287.9 1714.38   300.9 1711.69   327.1 1713.28   336.9 1714.96
   353.3 1712.52   383.9 1711.99   395.8 1711.24   408.9 1711.85   415.4 1712.25
     422 1714.14   425.2  1715.8   438.3 1725.72   448.1 1731.62   464.5 1739.68
   484.1 1746.54   490.7 1749.66   529.9 1772.17   556.1 1788.88   569.2 1795.41
#Mann= 5 ,-1 , 0
       0     .12       0  138.83     .06       0  211.18     .12       0
   383.9    .045       0   408.9     .12       0
#XS Ineff= 2 , 0
          281.46 1751.53
Permanent Ineff=
       F       F
Bank Sta=383.9,408.9
XS Rating Curve= 0 ,0
Exp/Cntr=0.3,0.1

Type RM Length L Ch R = 1 ,5658.5  ,385,382.7,377.7
XS GIS Cut Line= 4
     2022065.083       203762.64     2021899.938      203526.513
     2021882.035      203343.505     2021842.251      203271.894
#Sta/Elev= 30
       0 1758.27    45.8 1743.94    75.3 1736.28   111.3    1726   147.4  1717.6
  213.311711.906  242.15 1709.85   255.4 1708.82   317.2  1707.4   355.9 1707.38
   365.6 1706.12     372 1703.86   375.2 1703.53   381.7 1704.43   388.2 1703.82
   394.6 1702.36   405.8 1703.75     414  1704.9   430.1 1704.51   439.8 1706.55
   455.9  1706.6   462.4 1708.71   465.6 1710.49     472 1715.81   485.1 1732.84
   488.4  1736.6     495 1742.82   517.9 1761.73   537.6 1776.33     554 1790.11
#Mann= 5 ,-1 , 0
       0     .12       0  213.31     .06       0  242.15     .12       0
   388.2    .045       0   405.8     .12       0
Bank Sta=388.2,405.8
XS Rating Curve= 0 ,0
Exp/Cntr=0.3,0.1

Type RM Length L Ch R = 1 ,5275.8  ,311.8,307.1,303
XS GIS Cut Line= 3
     2022321.269      203630.948      2022244.88      203420.879
      2022191.06      203139.629
#Sta/Elev= 30
       0 1782.92    35.6 1766.86   100.4 1739.86   155.5 1720.02   165.2 1715.42
   171.7 1710.28   174.9 1708.49   181.4 1708.05   184.6 1707.13  193.661702.308
   197.6 1700.98   207.3  1700.2   233.3 1700.29   262.6 1698.72  302.391699.089
   340.7 1700.08   366.7 1699.03     370 1698.61   376.5 1695.53     383 1695.27
   392.6 1695.73   402.5 1697.24   412.3 1697.67   418.8 1699.62   425.3 1703.57
   451.3 1721.29   457.8  1724.7   470.8 1729.01   496.9 1736.13   509.9 1740.65
#Mann= 5 ,-1 , 0
       0     .12       0  193.66     .06       0  302.39     .12       0
   376.5    .045       0   392.6     .12       0
Bank Sta=376.5,392.6
XS Rating Curve= 0 ,0
Exp/Cntr=0.3,0.1

Type RM Length L Ch R = 1 ,4968.7  ,270.6,278.7,286.7
XS GIS Cut Line= 3
     2022618.144      203528.518     2022491.407      203143.101
     2022435.852      203058.032
#Sta/Elev= 30
       0  1776.3    16.4 1768.18    88.3 1729.49   111.2 1718.68   127.6 1711.52
   140.7 1705.39     144 1703.59   150.5 1698.95   153.8 1697.78   170.1 1694.47
   181.41693.448   232.3 1693.21   242.1 1692.86   274.8 1693.65  289.471693.551
   307.6 1693.82   310.8 1693.21   317.4 1690.31   320.6  1689.7   330.5 1690.11
     337 1691.82   346.8 1692.89   353.4 1693.03     373 1692.33   382.8  1692.7
   392.6  1695.8     409  1700.4   458.2 1716.18   474.6 1720.67   507.3 1732.28
#Mann= 5 ,-1 , 0
       0     .12       0   181.4     .06       0  289.47     .12       0
   317.4    .045       0   330.5     .12       0
Bank Sta=317.4,330.5
XS Rating Curve= 0 ,0
Exp/Cntr=0.3,0.1

Type RM Length L Ch R = 1 ,4690    ,276,267.7,258.3
XS GIS Cut Line= 2
     2022791.755      203490.323     2022730.991      202924.351
#Sta/Elev= 30
       0 1767.14    62.2 1738.01    94.9 1723.69   124.3 1711.92   134.1 1705.99
   147.2 1695.31   150.5 1693.53   160.3 1692.16   166.8 1690.42  175.181689.642
   222.5 1690.02   255.2 1688.01   268.3 1687.81  296.841688.599   340.2 1688.85
   353.3  1687.3   366.4 1687.64   379.5 1686.21     386 1685.59   395.8 1686.08
   402.4 1688.67   405.6 1689.13   451.4 1690.92   454.7 1692.04   467.8 1699.11
   474.4 1700.97   497.2 1704.74   533.2 1709.12   559.4 1714.59   569.2  1717.5
#Mann= 5 ,-1 , 0
       0     .12       0  175.18     .06       0  296.84     .12       0
   379.5    .045       0   395.8     .12       0
#XS Ineff= 2 , 0
          216.39 1690.33
Permanent Ineff=
       F       F
Bank Sta=379.5,395.8
XS Rating Curve= 0 ,0
Exp/Cntr=0.3,0.1

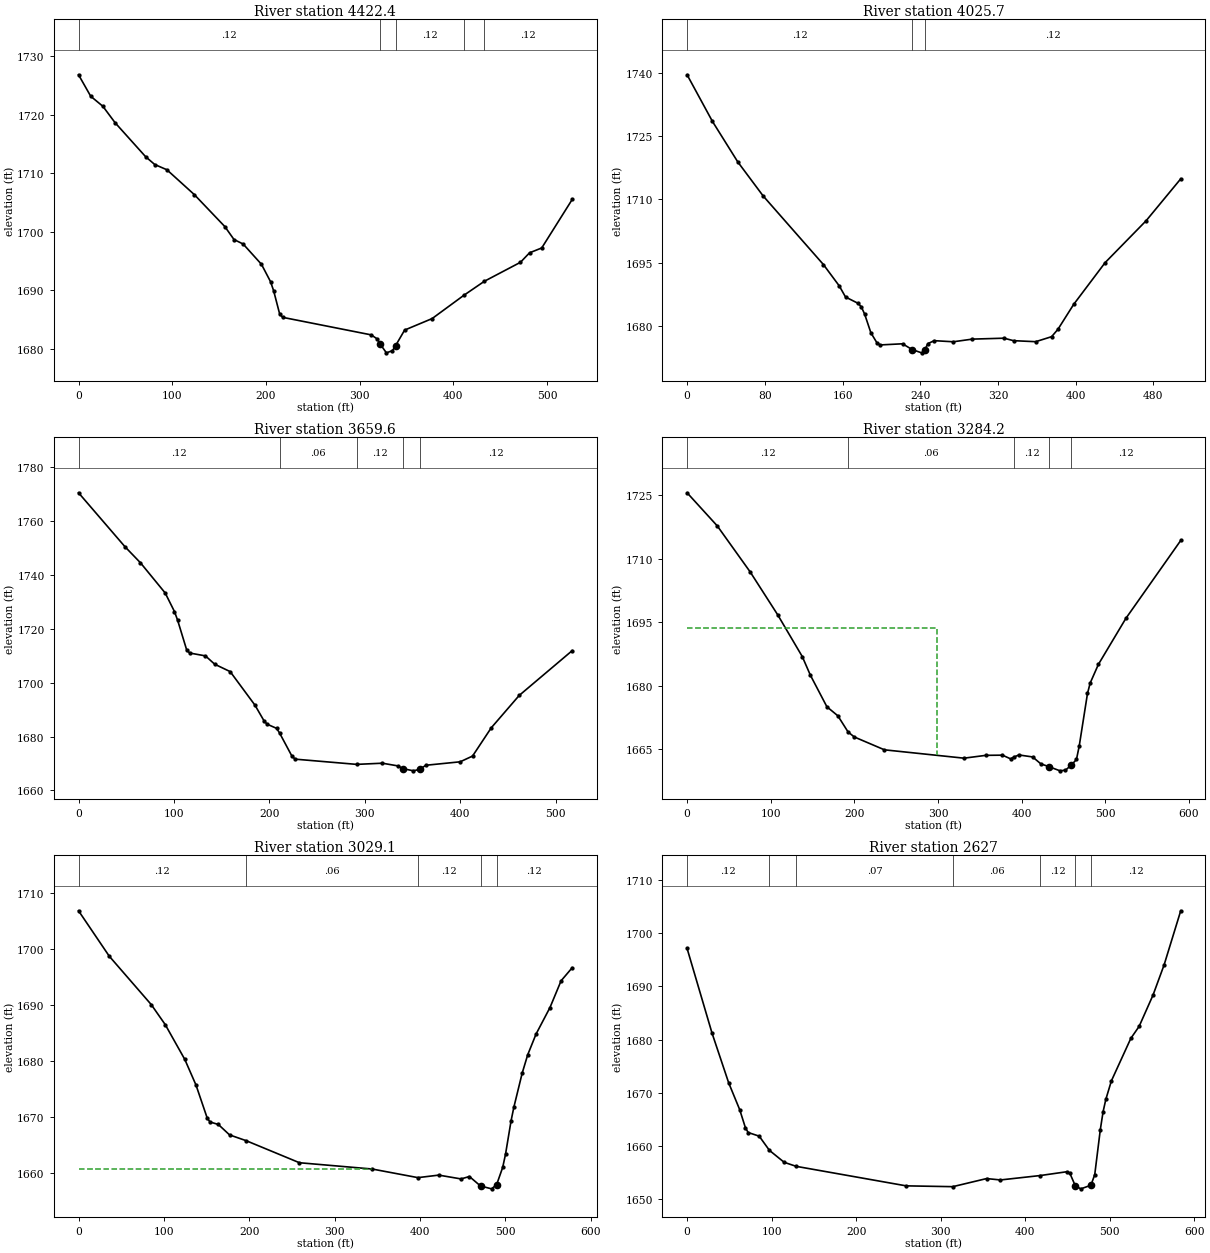
Type RM Length L Ch R = 1 ,4422.4  ,407.7,396.7,385.4
XS GIS Cut Line= 3
      2023213.63       203313.24     2023038.282       203148.31
      2022941.06      202879.212
#Sta/Elev= 30
       0 1726.81      13 1723.14      26 1721.42      39 1718.62    71.6 1712.81
    81.3 1711.48    94.3 1710.58   123.6 1706.33   156.2 1700.86   165.9 1698.66
   175.7 1697.89   195.2 1694.43   204.9 1691.46   208.2 1689.91   214.7  1685.9
     218 1685.36   312.3 1682.37   318.8 1681.67     322 1680.78   328.5  1679.3
     335 1679.67   338.3 1680.52     348 1683.19   377.3 1685.15  411.191689.129
  433.12 1691.53   471.6 1694.77   481.3 1696.39   494.3 1697.22   526.8  1705.5
#Mann= 5 ,-1 , 0
       0     .12       0     322    .045       0   338.3     .12       0
  411.19     .06       0  433.12     .12       0
Bank Sta=322,338.3
XS Rating Curve= 0 ,0
Exp/Cntr=0.3,0.1

Type RM Length L Ch R = 1 ,4025.7  ,360.5,366.1,370.9
XS GIS Cut Line= 3
     2023512.241      203101.435     2023279.602      202790.671
     2023234.463       202679.56
#Sta/Elev= 30
       0 1739.62    26.1 1728.54    52.2 1718.91    78.3 1710.83   140.3 1694.54
   156.6 1689.47   163.1 1686.82   176.2  1685.3   179.4 1684.45   182.7 1682.79
   189.2 1678.31   195.7 1675.83     199 1675.44   221.8 1675.71   231.6 1674.34
   241.4 1673.56   244.7 1674.32   247.9 1675.76   254.4 1676.45     274 1676.19
   293.6 1676.82   326.2 1677.04     336 1676.45   358.8 1676.21   375.2  1677.4
   381.7 1679.15   397.9 1685.07   430.3    1695   472.5 1704.95   508.1  1714.9
#Mann= 3 ,-1 , 0
       0     .12       0   231.6    .045       0   244.7     .12       0
Bank Sta=231.6,244.7
XS Rating Curve= 0 ,0
Exp/Cntr=0.3,0.1

Type RM Length L Ch R = 1 ,3659.6  ,376.6,375.4,373.5
XS GIS Cut Line= 3
     2023750.088       203023.31     2023720.574      202808.032
     2023574.741      202545.879
#Sta/Elev= 30
       0 1770.41    48.6 1750.43    64.9 1744.44    90.8 1733.25   100.5 1726.38
   103.8 1723.19   113.5 1711.92   116.8 1710.96     133 1709.92   142.7 1706.83
   158.9 1704.09   184.9 1691.64   194.6  1685.7   197.8 1684.56   207.6 1683.04
  210.631681.345   223.8 1672.63   227.1 1671.62  291.411669.686   318.4 1670.12
   334.7 1669.12     340  1668.1     351 1667.29   357.5 1667.86     364 1669.36
   399.9 1670.64   412.9 1672.77   432.5 1683.25   461.8 1695.26   517.3 1711.86
#Mann= 5 ,-1 , 0
       0     .12       0  210.63     .06       0  291.41     .12       0
     340    .045       0   357.5     .12       0
Bank Sta=340,357.5
XS Rating Curve= 0 ,0
Exp/Cntr=0.3,0.1

Type RM Length L Ch R = 1 ,3284.2  ,255.3,255.1,254.5
XS GIS Cut Line= 3
     2024177.584      202885.987     2024070.166      202661.206
     2023891.137      202370.781
#Sta/Elev= 30
       0 1725.59    36.1 1717.77    75.4 1706.92   108.2 1696.83   137.7 1686.94
   147.5  1682.5   167.2 1675.07   180.3 1672.94  192.561669.114     200 1667.94
     236 1664.91   331.1 1662.94   357.4 1663.61   377.1 1663.65   386.9 1662.78
  390.991663.228   396.8  1663.7   413.2 1663.23     423  1661.6   432.8 1660.93
     446 1659.95   452.5 1660.12   459.1 1661.24   465.6 1662.63   468.9 1665.79
   478.8 1678.22     482 1680.67   491.9  1685.1   524.7 1695.94   590.3 1714.33
#Mann= 5 ,-1 , 0
       0     .12       0  192.56     .06       0  390.99     .12       0
   432.8    .045       0   459.1     .12       0
#XS Ineff= 2 , 0
          298.87 1693.57
Permanent Ineff=
       F       F
Bank Sta=432.8,459.1
XS Rating Curve= 0 ,0
Exp/Cntr=0.3,0.1

Type RM Length L Ch R = 1 ,3029.1  ,397,402.2,406.3
XS GIS Cut Line= 3
     2024475.782      202709.073     2024248.352      202464.282
     2024118.144      202257.685
#Sta/Elev= 30
       0 1706.85      36 1698.74    85.2  1690.1   101.6 1686.52   124.5 1680.31
   137.6 1675.74   150.7 1669.86     154 1669.15   163.8  1668.7   176.9 1666.84
  196.261665.814   258.8 1661.87   343.9 1660.75  397.61 1659.21     422 1659.66
   448.1 1658.98   457.9 1659.41   470.9 1657.72   483.9 1657.21   489.8 1657.97
   496.9 1661.04   500.2 1663.38   506.7 1669.35     510  1671.8   519.7 1677.85
   526.2 1681.14     536 1684.85   552.3 1689.58   565.3 1694.35   578.3 1696.68
#Mann= 5 ,-1 , 0
       0     .12       0  196.26     .06       0  397.61     .12       0
   470.9    .045       0   489.8     .12       0
#XS Ineff= 2 , 0
          343.78  1660.8
Permanent Ineff=
       F       F
Bank Sta=470.9,489.8
XS Rating Curve= 0 ,0
Exp/Cntr=0.3,0.1

Type RM Length L Ch R = 1 ,2627    ,359.2,370.9,381.6
XS GIS Cut Line= 2
     2024712.681      202569.702     2024466.019      202040.572
#Sta/Elev= 30
       0 1697.13    29.5 1681.21    49.2 1671.86    62.3 1666.79    68.9 1663.46
    72.2 1662.53    85.3 1661.84   97.381659.172   114.8 1656.93  128.99 1656.17
   259.1  1652.5   314.21652.348   354.2 1653.87   370.6 1653.61  417.931654.446
   449.3 1655.16   452.6 1654.89   459.2 1652.48   465.7 1651.94   477.6 1652.62
   482.1 1654.61   488.7 1663.08     492 1666.46   495.2 1668.75   501.8 1672.24
   524.8 1680.23   534.6 1682.48     551 1688.35   564.1 1694.02   583.8 1704.21
#Mann= 7 ,-1 , 0
       0     .12       0   97.38     .06       0  128.99     .07       0
   314.2     .06       0  417.93     .12       0   459.2    .045       0
   477.6     .12       0
Bank Sta=459.2,477.6
XS Rating Curve= 0 ,0
Exp/Cntr=0.3,0.1

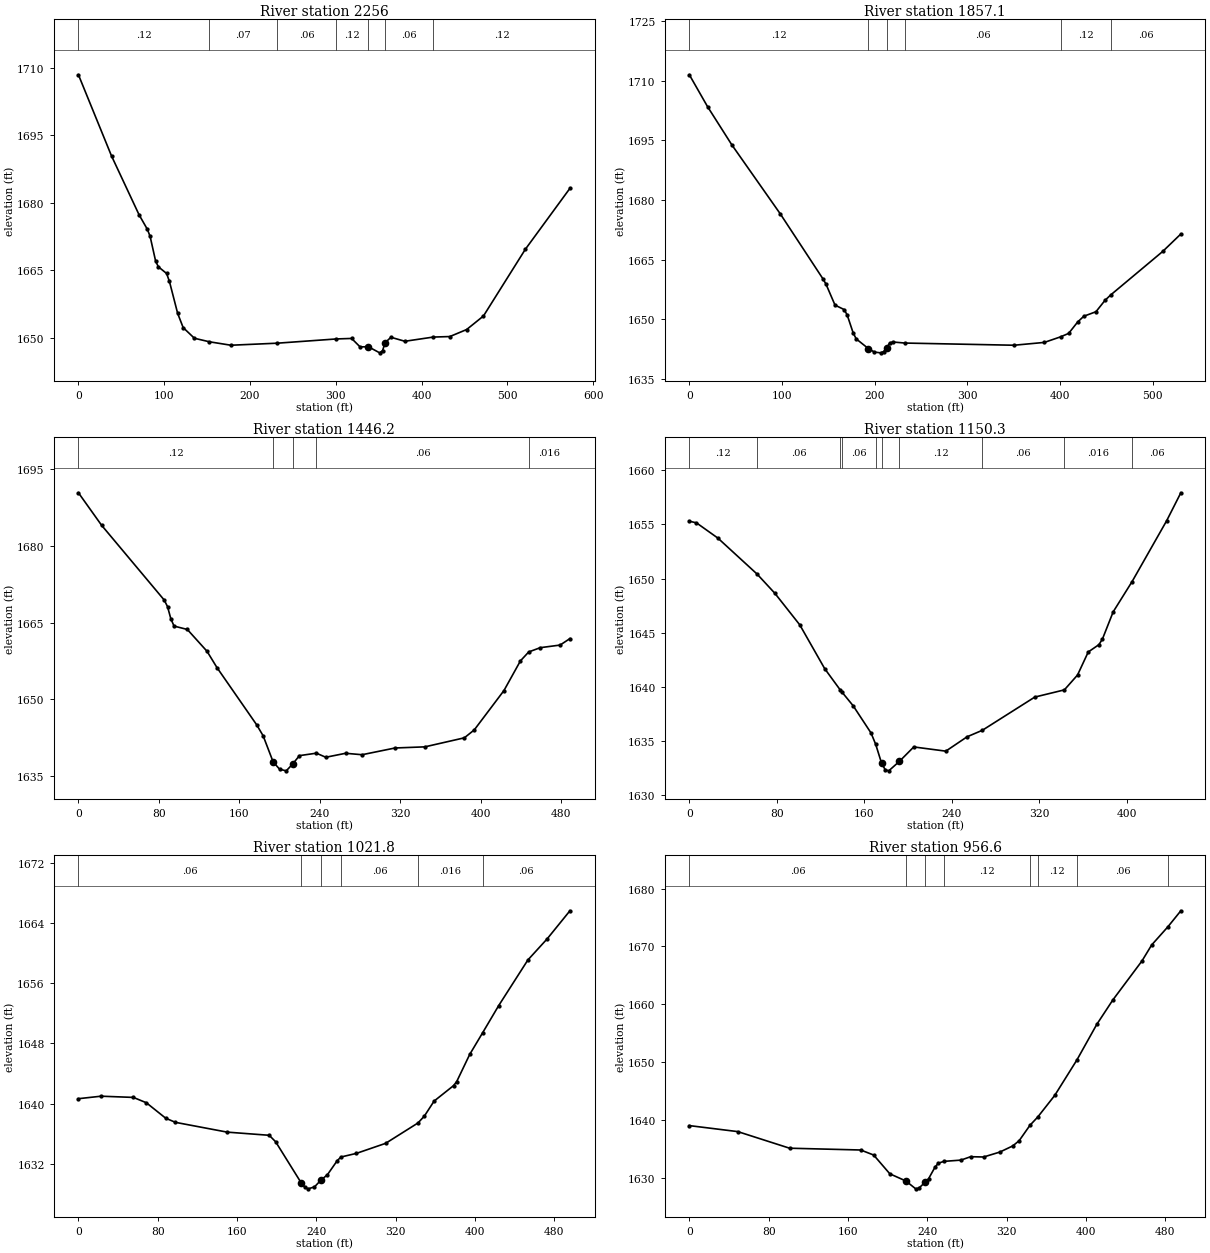
Type RM Length L Ch R = 1 ,2256    ,407.4,398.9,389
XS GIS Cut Line= 4
      2024969.29      202452.339     2024907.624      202346.911
     2024863.861      202012.723     2024812.142      201911.274
#Sta/Elev= 30
       0 1708.44    38.6 1690.39    70.7 1677.32    80.4 1674.08    83.6  1672.5
      90 1667.02    93.2 1665.76   102.8 1664.28   106.1  1662.5   115.7  1655.4
   122.1 1652.25   135.2 1649.88  152.761649.093   177.8 1648.33  231.871648.786
  300.671649.727   318.5 1649.84   328.3 1647.97   338.1 1647.99   351.2 1646.64
   354.5 1647.12   357.7 1648.91   364.3  1650.1   380.6 1649.21  413.711650.146
     433 1650.26   452.6 1651.82   472.2 1654.83     521 1669.65     573  1683.2
#Mann= 7 ,-1 , 0
       0     .12       0  152.76     .07       0  231.87     .06       0
  300.67     .12       0   338.1    .045       0   357.7     .06       0
  413.71     .12       0
Bank Sta=338.1,357.7
XS Rating Curve= 0 ,0
Exp/Cntr=0.3,0.1

Type RM Length L Ch R = 1 ,1857.1  ,426.7,410.9,393.4
XS GIS Cut Line= 2
     2025317.401      202291.213     2025122.459      201797.889
#Sta/Elev= 30
       0 1711.45    19.6 1703.46    45.8 1693.86    98.2 1676.48   144.1  1660.2
   147.4 1658.88   157.2 1653.57     167 1652.46   170.3 1651.12   176.8 1646.58
   180.1 1645.08   193.2 1642.65   199.7 1641.77   206.3 1641.58   209.6 1641.88
   212.8 1642.84   216.1 1644.01   219.4 1644.31  232.57 1644.04   350.4 1643.49
   383.1  1644.2  400.571645.597   409.3 1646.46   419.1 1649.34   425.7 1650.78
   438.8 1651.91   448.6 1654.78  454.751656.135   510.8 1667.05   530.4 1671.44
#Mann= 6 ,-1 , 0
       0     .12       0   193.2    .045       0   212.8     .12       0
  232.57     .06       0  400.57     .12       0  454.75     .06       0
Bank Sta=193.2,212.8
XS Rating Curve= 0 ,0
Exp/Cntr=0.3,0.1

Type RM Length L Ch R = 1 ,1446.2  ,312.7,295.9,277.9
XS GIS Cut Line= 2
     2025710.157      202005.948     2025354.255      201670.879
#Sta/Elev= 30
       0 1690.43      23 1684.07    85.3 1669.41    88.6 1668.12    91.9 1665.74
    95.1  1664.3   108.3 1663.64   127.9 1659.36   137.8 1656.16   177.2 1644.97
   183.7  1642.8   193.6  1637.7   200.1 1636.24   206.7 1635.93   213.2  1637.3
   219.8 1638.91  236.681639.391     246 1638.59   265.7 1639.37   282.1 1639.09
   314.9 1640.41   344.5 1640.63   383.8  1642.4   393.7 1643.96   423.2 1651.67
   439.6 1657.49  447.841659.235   459.3 1660.07     479 1660.58   488.8 1661.85
#Mann= 5 ,-1 , 0
       0     .12       0   193.6    .045       0   213.2     .12       0
  236.68     .06       0  447.84    .016       0
Bank Sta=193.6,213.2
XS Rating Curve= 0 ,0
Exp/Cntr=0.3,0.1

Type RM Length L Ch R = 1 ,1150.3  ,137.7,128.6,119.9
XS GIS Cut Line= 2
     2025918.925      201689.976     2025489.237      201557.598
#Sta/Elev= 30
       0  1655.3     6.5 1655.15    26.1 1653.74   61.951650.415    78.2 1648.64
     101 1645.72   123.8 1641.67  137.74 1639.74  139.721639.488   149.9 1638.23
   166.2 1635.72  170.461634.673   175.9 1632.91   179.2 1632.32   182.4 1632.22
   192.2  1633.1   205.3 1634.43   234.6 1634.04   254.1 1635.37     2681635.968
     316 1639.04  343.061639.706   355.1 1641.08   364.9 1643.21   374.7 1643.89
   377.9 1644.41   387.7 1646.92  404.991649.717   436.6 1655.34   449.6 1657.93
#Mann= 10 ,-1 , 0
       0     .12       0   61.95     .06       0  137.74     .12       0
  139.72     .06       0  170.46     .12       0   175.9    .045       0
   192.2     .12       0     268     .06       0  343.06    .016       0
  404.99     .06       0
Bank Sta=175.9,192.2
XS Rating Curve= 0 ,0
Exp/Cntr=0.3,0.1

Type RM Length L Ch R = 1 ,1021.8  ,64.9,65.1,64.9
XS GIS Cut Line= 2
     2026010.505      201526.782     2025515.713      201497.268
#Sta/Elev= 30
       0 1640.67    22.8    1641    55.4 1640.84    68.5 1640.13      88 1638.08
    97.8 1637.53     150 1636.23   192.4 1635.81   198.9 1634.95   224.5 1629.53
   228.3 1628.92   231.5  1628.7     238 1628.95   244.6 1629.86   251.1 1630.57
   260.9 1632.42  264.681632.922   280.4 1633.41   309.8 1634.74  342.461637.447
   348.9 1638.36   358.7 1640.35   378.3  1642.4   381.5 1642.94   394.6 1646.54
  407.571649.403   423.9 1653.04   453.3 1659.09   472.8  1661.9   495.7 1665.62
#Mann= 6 ,-1 , 0
       0     .06       0   224.5    .045       0   244.6     .12       0
  264.68     .06       0  342.46    .016       0  407.57     .06       0
Bank Sta=224.5,244.6
XS Rating Curve= 0 ,0
Exp/Cntr=0.3,0.1

Type RM Length L Ch R = 1 ,956.6   ,100.6,114.9,129.5
XS GIS Cut Line= 2
     2026027.866      201464.282     2025533.074      201434.768
#Sta/Elev= 30
       0    1639    48.9 1637.96   101.1 1635.09   172.8 1634.78   185.9 1633.91
   202.2 1630.66   218.5 1629.41   228.3 1628.06   231.5 1628.18     238 1629.23
   241.3 1629.82   247.8 1631.82   251.1 1632.49  256.621632.812   273.9 1633.03
   283.7 1633.62   296.8 1633.57   313.1 1634.42   326.1 1635.48   332.6 1636.38
  343.541639.058  351.391640.487   368.5 1644.22  390.861650.354   410.9 1656.51
   427.2 1660.76   456.5 1667.49   466.3 1670.26  482.641673.399   495.7 1676.17
#Mann= 8 ,-1 , 0
       0     .06       0   218.5    .045       0     238     .06       0
  256.62     .12       0  343.54     .06       0  351.39     .12       0
  390.86     .06       0  482.64     .12       0
Bank Sta=218.5,238
XS Rating Curve= 0 ,0
Exp/Cntr=0.3,0.1

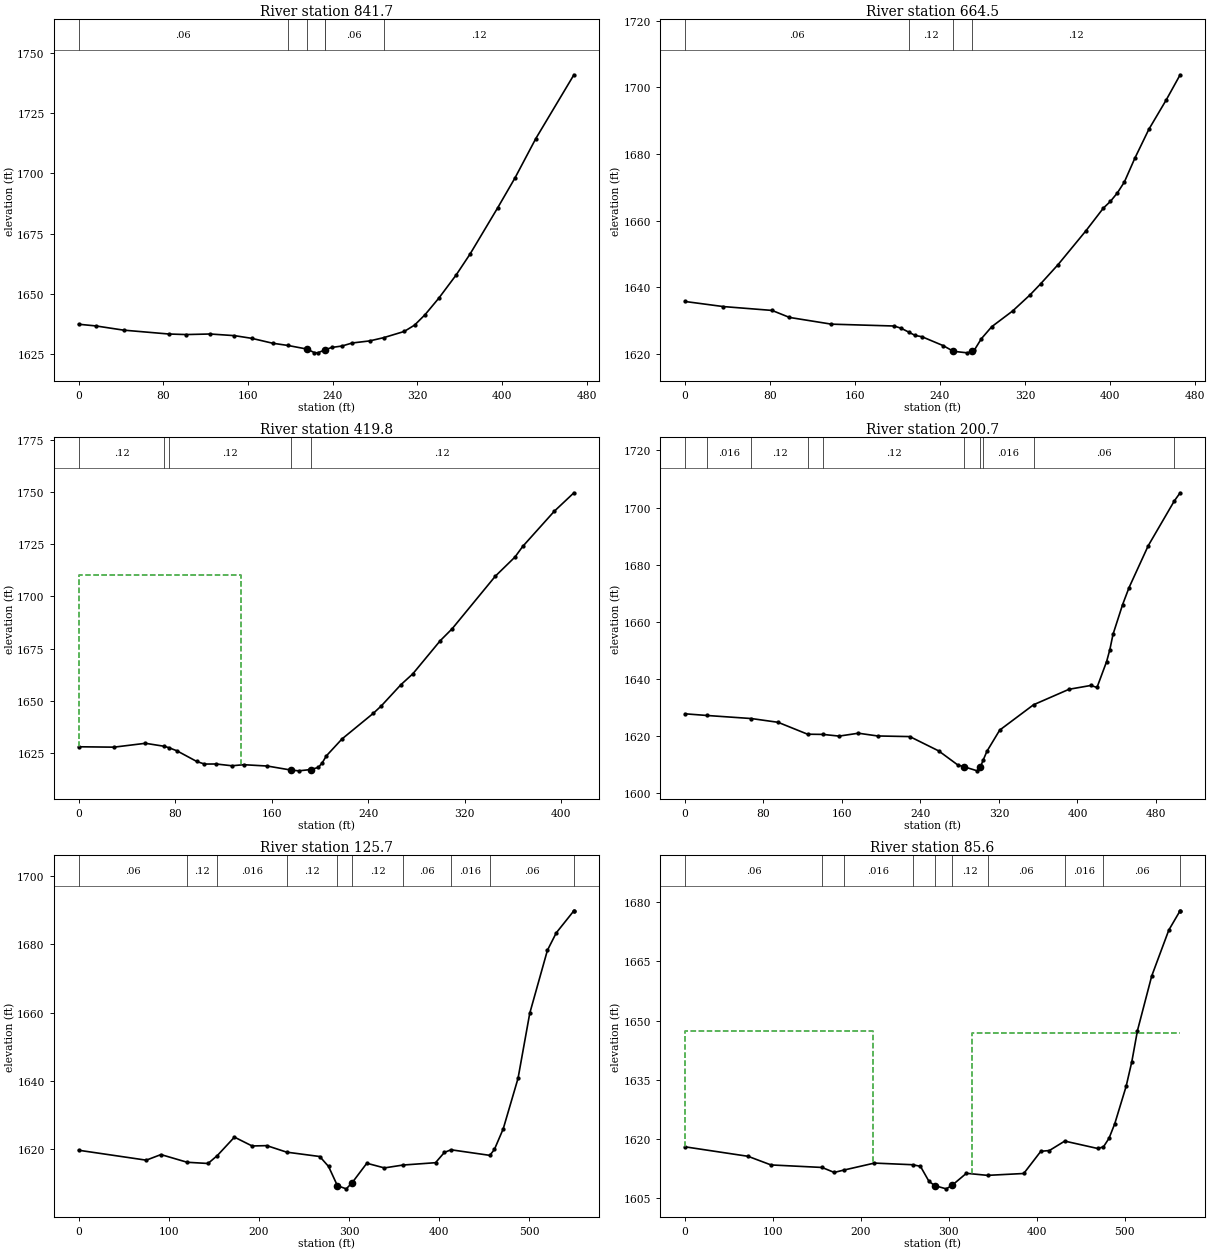
Type RM Length L Ch R = 1 ,841.7   ,166.5,177.2,187.7
XS GIS Cut Line= 2
     2026025.262        201433.9     2025602.085      201234.247
#Sta/Elev= 30
       0 1637.48    16.4 1636.77    42.5 1635.03    85.1 1633.43   101.4  1633.2
   124.3 1633.43   147.2 1632.75   163.6 1631.63   183.2 1629.61  197.611628.687
     216 1627.16   222.5 1625.73   225.8 1625.62   232.3 1626.76   232.61626.814
   238.9 1627.84   248.7 1628.44   258.5 1629.71   274.9 1630.56  288.131631.909
   307.6 1634.49   317.4 1637.13   327.2 1641.41   340.3 1648.31   356.7 1657.94
   369.8  1666.6   395.9 1685.77   412.3  1698.2   431.9 1714.47   467.9  1740.9
#Mann= 6 ,-1 , 0
       0     .06       0  197.61     .12       0     216    .045       0
   232.3     .12       0   232.6     .06       0  288.13     .12       0
Bank Sta=216,232.3
XS Rating Curve= 0 ,0
Exp/Cntr=0.3,0.1

Type RM Length L Ch R = 1 ,664.5   ,235.9,244.7,253.3
XS GIS Cut Line= 2
     2026092.536      201351.435     2025743.144      201043.275
#Sta/Elev= 30
       0 1635.75    36.1 1634.22      82 1633.06    98.4 1630.96   137.8 1628.94
   196.8 1628.38   203.4 1627.72  210.611626.553   216.5 1625.56   223.1 1625.16
   242.8 1622.52   252.6 1620.79   265.7 1620.33   270.2 1620.76   272.3 1621.15
   278.9 1624.56   288.7 1628.18   308.4 1632.91   324.8 1637.75   334.6 1641.02
     351 1646.78   377.3 1656.97   393.7 1663.77   400.3 1665.78   406.8 1668.31
   413.4 1671.58   423.2 1678.68   436.4 1687.38   452.8 1696.23   465.9 1703.78
#Mann= 4 ,-1 , 0
       0     .06       0  210.61     .12       0   252.6    .045       0
   270.2     .12       0
Bank Sta=252.6,270.2
XS Rating Curve= 0 ,0
Exp/Cntr=0.3,0.1

Type RM Length L Ch R = 1 ,419.8   ,169.9,219.1,250.3
XS GIS Cut Line= 2
     2026199.741      201186.938     2025961.025      200852.737
#Sta/Elev= 30
       0 1628.01    29.3 1627.82    55.4 1629.67   71.031628.237   74.781627.581
    81.5 1626.08    97.8 1621.01   104.3 1619.73   114.1 1619.76   127.1 1618.91
   136.9 1619.42   156.5 1618.78     176 1616.86   182.5 1616.48   192.3 1617.09
   198.8 1618.12   202.1 1620.41   205.4 1623.63   218.4 1631.76   244.5 1644.11
     251  1647.6   267.3 1657.78   277.1 1662.94   299.9 1678.85   309.7 1684.52
   345.5  1709.7   361.8 1718.88   368.3 1724.01   394.4 1740.81   410.7 1749.66
#Mann= 5 ,-1 , 0
       0     .12       0   71.03     .06       0   74.78     .12       0
     176    .045       0   192.3     .12       0
#XS Ineff= 2 , 0
           134.3  1710.2
Permanent Ineff=
       F       F
Bank Sta=176,192.3
XS Rating Curve= 0 ,0
Exp/Cntr=0.3,0.1

Type RM Length L Ch R = 1 ,200.7   ,92.3,75.1,73.7
XS GIS Cut Line= 4
     2026216.553      201170.568     2026253.329      200822.184
      2026258.19       200752.74     2026201.038      200690.222
#Sta/Elev= 30
       0 1627.82   22.57 1627.23   67.831626.154      95 1624.84  125.06 1620.67
  140.661620.604   157.2 1620.01   176.8 1621.02   196.4 1620.06   229.2 1619.84
   258.6 1614.83   278.3 1609.85   284.8 1609.24   297.9 1607.85   301.2 1609.27
  304.031611.697   307.8 1614.72   320.8 1622.12  355.291630.988   391.4  1636.4
   413.6 1637.74   419.9 1637.04   429.7 1646.12     433 1650.31   436.2 1655.63
     446 1666.07   452.5 1671.97   472.1 1686.67  498.621702.314   504.6 1705.19
#Mann= 10 ,-1 , 0
       0     .12       0   22.57    .016       0   67.83     .12       0
  125.06     .06       0  140.66     .12       0   284.8    .045       0
   301.2     .12       0  304.03    .016       0  355.29     .06       0
  498.62     .12       0
Bank Sta=284.8,301.2
XS Rating Curve= 0 ,0
Exp/Cntr=0.3,0.1

Type RM Length L Ch R = 1 ,125.7   ,47.8,40,33.5
XS GIS Cut Line= 4
     2026278.185      201143.658     2026314.492      200809.701
      2026319.31      200750.023     2026214.058      200638.261
#Sta/Elev= 30
       0 1619.69      75 1616.78    91.3 1618.42  120.371616.164   143.5 1615.81
  153.771618.117   172.8 1623.53   192.4 1620.94   208.7 1621.04  230.691619.132
   267.4 1617.85   277.2 1614.93     287  1609.3   296.8 1608.38   303.3 1610.16
   319.6 1615.88   339.1 1614.51  359.711615.351   395.8 1616.04   405.6 1619.04
  412.951619.824  456.031618.188   461.1 1619.92   470.9 1625.97   487.3 1640.74
   500.3 1659.82   519.9 1678.28   529.7 1683.38  548.931689.745   549.3 1689.85
#Mann= 10 ,-1 , 0
       0     .06       0  120.37     .12       0  153.77    .016       0
  230.69     .12       0     287    .045       0   303.3     .12       0
  359.71     .06       0  412.95    .016       0  456.03     .06       0
  548.93     .12       0
Bank Sta=287,303.3
XS Rating Curve= 0 ,0
Exp/Cntr=0.3,0.1

Type RM Length L Ch R = 1 ,85.6    ,98.9,85.6,72.3
XS GIS Cut Line= 3
     2026349.909      201124.285     2026345.352      200748.938
     2026219.484      200610.049
#Sta/Elev= 30
       0 1617.99    71.8 1615.58    97.9 1613.39  155.911612.752   169.7 1611.49
  180.581612.082   215.4 1613.86  258.831613.442   267.7 1613.04   277.4 1609.23
     284 1608.14     297 1607.33   303.6 1608.21   319.9 1611.27  343.911610.746
   385.1 1611.22   404.5 1616.85   414.2 1617.04  431.661619.437   469.1 1617.56
  475.651617.973     482 1620.16   488.5 1623.84   501.4  1633.3   507.9 1639.59
   514.3 1647.46   530.5  1661.3   549.9 1672.93  562.271677.656   562.8 1677.83
#Mann= 10 ,-1 , 0
       0     .06       0  155.91     .12       0  180.58    .016       0
  258.83     .12       0     284    .045       0   303.6     .12       0
  343.91     .06       0  431.66    .016       0  475.65     .06       0
  562.27     .12       0
#XS Ineff= 2 , 0
          214.12 1647.35   326.1         1646.84
Permanent Ineff=
       F       F
Bank Sta=284,303.6
XS Rating Curve= 0 ,0
Exp/Cntr=0.3,0.1

Chan Stop Cuts=-1
Use User Specified Reach Order=0
Composite Channel Slope=5